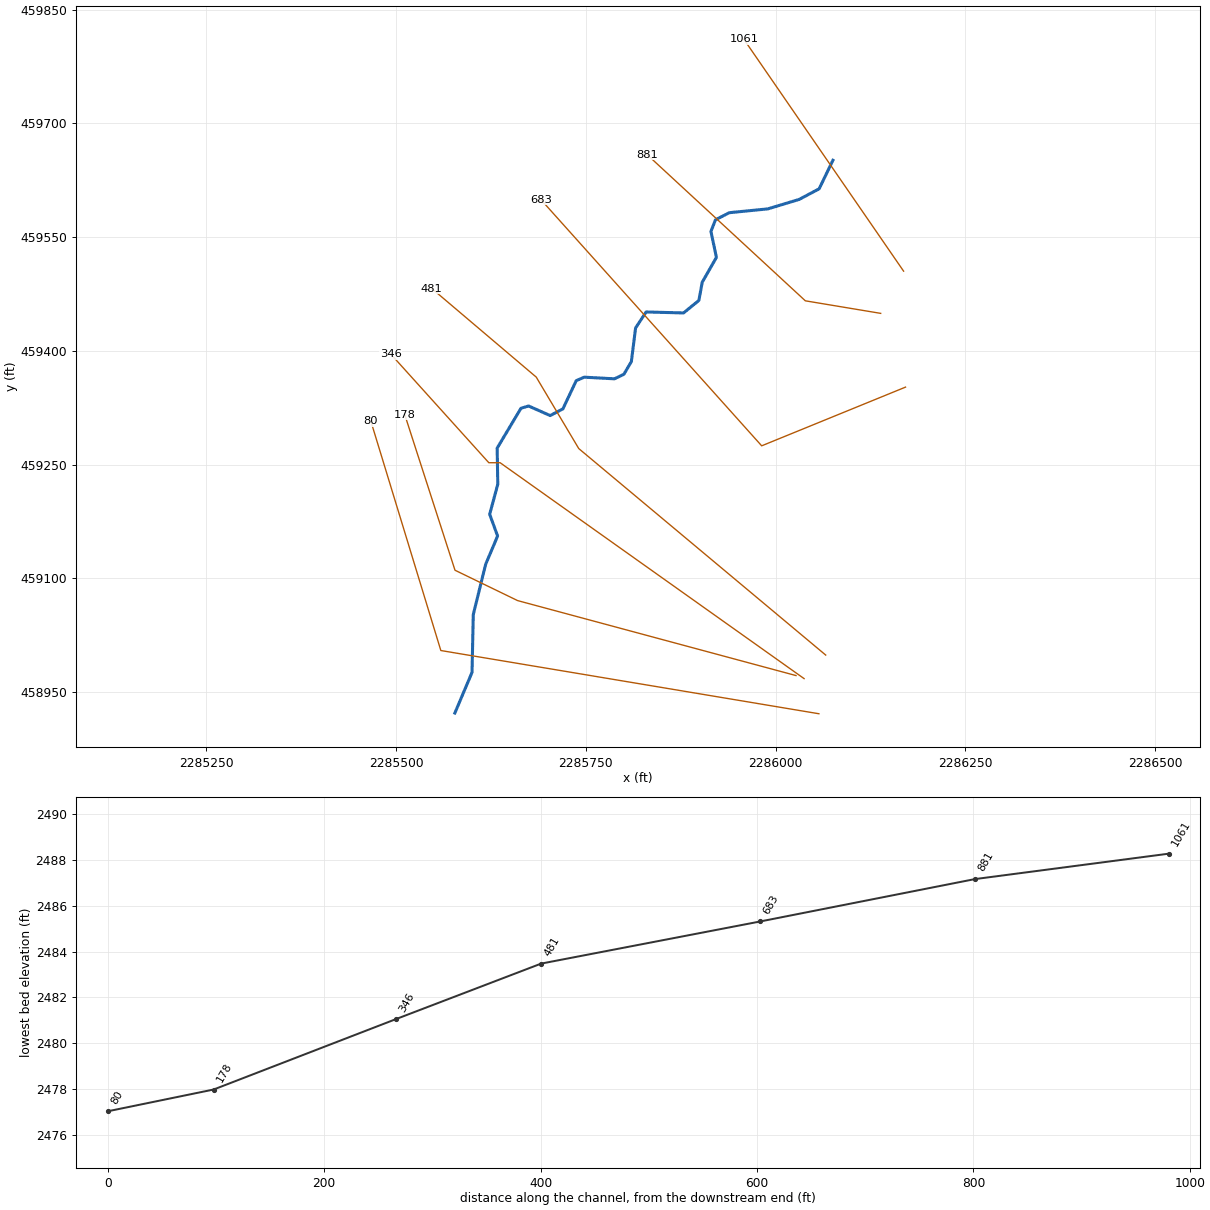
--- KNAPPCKT3.prj (project) ---

Proj Title=KNAPPCKT3
Current Plan=p01
Default Exp/Contr=0,0
English Units
Geom File=g01
Flow File=f01
Plan File=p01
Background Map Layer=Inundation Boundary (01pct Value_0)
BEGIN DESCRIPTION:
----------MODEL BY WOOD PLC 2021----------
Stream Name: Knapp Creek Tributary 3
Flood Zone: Enhanced Approximate
Pocahontas County, WV
HEC-RAS Version: RAS 6.1
Vertical Datum: NAVD88
Projection: NAD 1983 StatePlane West Virginia S FIPS 4702 (US Feet)
Terrain: 1-meter LIDAR (FEMA Region III 3DEP collected 2016-2018)
Land Use: 2019 NLCD
Hydrologic Method:
WV SIR2010-5033 regression equations
Model Notes:
Normal depth tie in to Knapp Creek
END DESCRIPTION:
DSS File=dss
DSS Export Rating Curves= 0
DSS Export Rating Curve Sorted= 0
DSS Export Volume Flow Curves= 0
DXF OffsetX= 0
DXF OffsetY= 0
DXF ScaleX= 0
DXF ScaleY= 0

--- KNAPPCKT3.p01 (plan) ---

Plan Title=Floodplain
Program Version=6.10
Short Identifier=Floodplain
Geom File=g01
Flow File=f01
Subcritical Flow
K Sum by GR= 0
Std Step Tol= 0.01
Critical Tol= 0.01
Num of Std Step Trials= 20
Max Error Tol= 0.3
Flow Tol Ratio= 0.001
Split Flow NTrial= 30
Split Flow Tol= 0.02
Split Flow Ratio= 0.02
Log Output Level= 0
Friction Slope Method= 1
Unsteady Friction Slope Method= 2
Unsteady Bridges Friction Slope Method= 1
Parabolic Critical Depth
Global Vel Dist= 0 , 0 , 0
Global Log Level= 0
CheckData=True
Encroach Param=-1 ,0,0, 0
Computation Interval=0.1SEC
Output Interval=1SEC
Instantaneous Interval=Max Profile
Mapping Interval=1HOUR
Computation Time Step Use Courant=        0
Computation Time Step Use Time Series=    0
Computation Time Step Count To Double=0
Computation Time Step Max Doubling=0
Computation Time Step Max Halving=0
Computation Time Step Residence Courant=0
Run HTab= 0
Run UNet= 0
Run Sediment= 0
Run PostProcess= 0
Run WQNet= 0
Run RASMapper=-1
UNET Theta= 0
UNET Theta Warmup= 0
UNET ZTol= 0
UNET ZSATol= 0
UNET MxIter= 0
UNET Max Iter WO Improvement= 0
UNET MaxInSteps= 0
UNET DtIC= 0
UNET DtMin= 0
UNET MaxCRTS= 0
UNET WFStab= 0
UNET SFStab= 0
UNET WFX= 1
UNET SFX= 1
UNET Gravity=32.174
UNET 1D Methodology=Finite Difference
UNET DSS MLevel= 1
UNET Pardiso=0
UNET DZMax Abort= 0
UNET Use Existing IB Tables= 0
UNET Froude Reduction=False
UNET Froude Limit= 0
UNET Froude Power= 0
UNET D1 Cores= 0
UNET WindReference=Eulerian
UNET WindDragFormulation=Hsu (1988)
UNET D2 Coriolis=0
UNET D2 Cores= 0
UNET D2 Theta= 1
UNET D2 Theta Warmup= 1
UNET D2 Z Tol= 0.01
UNET D2 Volume Tol= 0.01
UNET D2 Max Iterations= 20
UNET D2 Equation= 0
UNET D2 RampUpFraction=0.1
UNET D2 TimeSlices= 1
UNET D2 Turbulence Formulation=Non-Conservative (original)
UNET D2 Eddy Viscosity=0.3
UNET D2 Transverse Eddy Viscosity=0.1
UNET D2 Smagorinsky Mixing=0
UNET D2 BCVolumeCheck=0
UNET D2 Cores=0
UNET D2 SolverType=PARDISO (Direct)
UNET D2 Minimum Iterations= 2147483647
UNET D2 Maximum Iterations= 2147483647
UNET D2 Restart Number= 10
UNET D2 Relaxation Coeff=1.3
UNET D2 SOR Precondition Iterations= 10
UNET D2 ILUT Maximum Fill= 8
UNET D2 ILUT Tolerance=1E-08
UNET D1D2 MaxIter= 0
UNET D1D2 ZTol=0.01
UNET D1D2 QTol=0.1
UNET D1D2 MinQTol=1
DSS File=dss
Write IC File= 0
Write IC File at Fixed DateTime=0
Write IC File at Sim End=0
Echo Input=False
Echo Parameters=False
Echo Output=False
Write Detailed= 0
HDF Write Warmup=0
HDF Write Time Slices=0
HDF Flush=0
HDF Compression= 1
HDF Chunk Size= 1
HDF Spatial Parts= 1
HDF Use Max Rows=0
HDF Fixed Rows= 1
Calibration Method= 0
Calibration Iterations= 20
Calibration Max Change=0.05
Calibration Tolerance=0.2
Calibration Maximum=1.5
Calibration Minimum=0.5
Calibration Optimization Method= 1
WQ AD Non Conservative
WQ ULTIMATE=-1
WQ Max Comp Step=1HOUR
WQ Output Interval=15MIN
WQ Output Selected Increments= 0
WQ Output face flow=0
WQ Output face velocity=0
WQ Output face area=0
WQ Output face dispersion=0
WQ Output cell volume=0
WQ Output cell surface area=0
WQ Output cell continuity=0
WQ Output cumulative cell continuity=0
WQ Output face conc=0
WQ Output face dconc_dx=0
WQ Output face courant=0
WQ Output face peclet=0
WQ Output face adv mass=0
WQ Output face disp mass=0
WQ Output cell mass=0
WQ Output cell source sink temp=0
WQ Output nsm pathways=0
WQ Output nsm derived pathways=0
WQ Create Restart=0
WQ Fixed Restart=0
WQ System Summary=0
WQ Write To DSS=0
Sorting and Armoring Iterations= 10
XS Update Threshold= 0.02
Bed Roughness Predictor= 0
Hydraulics Update Threshold= 0.02
Energy Slope Method= 1
Volume Change Method= 1
Sediment Retention Method= 0
Sediment TS Multiplier= 1
Warm Up Method= 0
XS Weighting Method= 0
Number of US Weighted Cross Sections= 1
Number of DS Weighted Cross Sections= 1
Upstream XS Weight=0
Main XS Weight=1
Downstream XS Weight=0
Number of DS XS's Weighted with US Boundary= 1
Upstream Boundary Weight= 1
Weight of XSs Associated with US Boundary= 0
Number of US XS's Weighted with DS Boundary= 1
Downstream Boundary Weight= 0.5
Weight of XSs Associated with DS Boundary= 0.5
Percentile Method= 0
Sediment Output Level= 3
Mass or Volume Output= 0
Output Increment Type= 1
Profile and TS Output Increment= 1
Transport Output Increment 1
XS Output Flag= 0
XS Output Increment= 10
Read HDF5 Sediment Hotstart= 0
Sediment Hotstart Type= 0
Write Gradation File= 0
Read Gradation Hotstart= 0
Write HDF5 File= 1
Write Binary Output= 1
Write DSS Sediment File= 0
DSS Sediment Output Type= 1
SV Curve= 0
Specific Gage Flag= 0
Subcell Erosion Methods= 0
Subcell Deposition Methods= 0
Advection Scheme= 1
Matrix Solver= 0
Implicit Weighting Factor= 1
Maximum Outer Loop Convergence Iterations= 5
Convergence Maximum Absolute= 0.001
Convergence RMSE= 0.0001
Grain Fractions Max Abs Error= 0.001
Max Subgrid Regions= 1
Max Subgrid Length Scale= 3.402823E+38
Initial Layer Thickness= 3.402823E+38
Min Layer Thickness= 3.402823E+38
Max Layer Thickness= 3.402823E+38
Number of Layers= 5

--- KNAPPCKT3.f01 (steady flow) ---

Flow Title=Flow
Program Version=6.10
Number of Profiles= 6
Profile Names=01pct,10pct,04pct,02pct,0_2pct,01plus
River Rch & RM=KNAPPCKT3,Main,1061
     197     100     136     165     281     292
Boundary for River Rch & Prof#=KNAPPCKT3,Main            , 1
Up Type= 0
Dn Type= 3
Dn Slope=0.011069
Boundary for River Rch & Prof#=KNAPPCKT3,Main            , 2
Up Type= 0
Dn Type= 3
Dn Slope=0.011069
Boundary for River Rch & Prof#=KNAPPCKT3,Main            , 3
Up Type= 0
Dn Type= 3
Dn Slope=0.011069
Boundary for River Rch & Prof#=KNAPPCKT3,Main            , 4
Up Type= 0
Dn Type= 3
Dn Slope=0.011069
Boundary for River Rch & Prof#=KNAPPCKT3,Main            , 5
Up Type= 0
Dn Type= 3
Dn Slope=0.011069
Boundary for River Rch & Prof#=KNAPPCKT3,Main            , 6
Up Type= 0
Dn Type= 3
Dn Slope=0.011069
DSS Import GetInterval= 0
DSS Import GetPeak= 0
DSS Import FillOption= 0

--- KNAPPCKT3.g01 (geometry) ---

Geom Title=Geometry
Program Version=6.10

River Reach=KNAPPCKT3       ,Main
Reach XY= 30
 2286075.6492696 459651.306187942286057.44238796459613.610249901
     2286031.133      459599.626     2285989.687      459587.122
     2285939.083       459582.13     2285920.835      459572.806
     2285914.837      459557.433     2285922.064      459523.165
     2285903.377       459490.44     2285898.908      459466.349
     2285878.751      459449.917     2285829.432      459451.195
     2285815.542      459430.138     2285809.945      459385.675
      2285800.05      459368.958     2285787.678      459363.029
     2285747.864      459365.186     2285737.328      459360.621
     2285719.731      459323.384     2285703.007      459314.551
     2285674.538      459327.159     2285664.518      459324.218
      2285633.09       459271.63     2285633.912      459223.973
2285623.22276885459184.335158762     2285633.679      459155.702
     2285617.887      459118.282      2285601.61      459052.055
     2285599.977      458975.872     2285577.339      458922.187

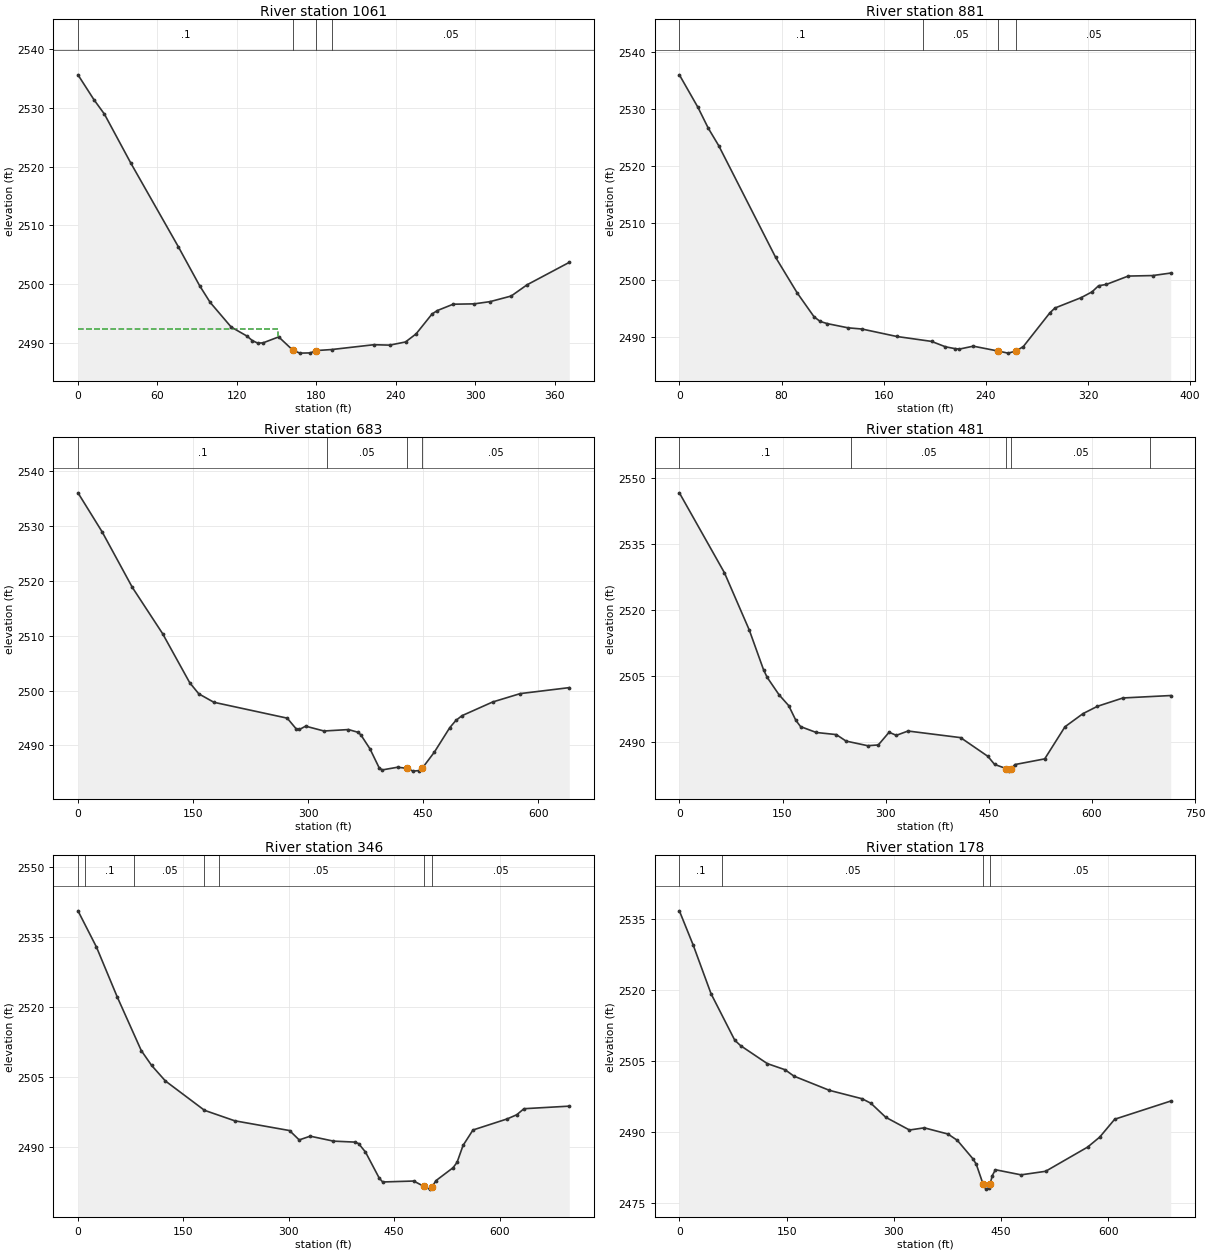
Type RM Length L Ch R = 1 ,1061    ,177.6,179.1,174.2
XS GIS Cut Line= 2
2286168.74520413459505.0337905162285958.31320413459810.755790516
#Sta/Elev= 30
       0 2535.61      12  2531.4      20 2528.92    39.9  2520.6    75.8 2506.37
    91.8 2499.78    99.8 2496.92   115.7 2492.72   127.7 2491.17   131.7 2490.41
   135.7 2489.99   139.7 2490.02   151.6 2491.04  162.28 2488.78   167.6 2488.28
   175.6 2488.32   179.6 2488.71   191.6 2488.89   223.5 2489.71   235.5 2489.64
   247.4 2490.18   255.4 2491.56   267.4 2494.93   271.4 2495.52   283.4  2496.6
   299.3 2496.66   311.3 2497.04   327.2 2497.99   339.2  2499.9   371.1 2503.72
#Mann= 4 ,-1,0
       0      .1       0  162.28    .045       0   179.6      .1       0
   191.6     .05       0
#XS Ineff= 2 , 0
          151.34 2492.33
Permanent Ineff=
       F       F
Bank Sta=162.28,179.6
XS Rating Curve= 0 ,0
Exp/Cntr=0.3,0.1

Type RM Length L Ch R = 1 ,881     ,196.4,198.3,192.4
XS GIS Cut Line= 3
2286138.58249853459449.3471016052286039.25929933459465.900968137
2285830.68058103459658.753513239
#Sta/Elev= 30
       0    2536    14.6 2530.27    22.7 2526.61    30.8 2523.58    75.4 2503.97
    92.3 2497.73   105.5 2493.54   110.3 2492.73   115.8 2492.35   132.1 2491.61
     143  2491.4   170.3 2490.09   197.5 2489.23   208.4 2488.28   215.6 2487.97
   219.3 2487.88   230.2 2488.39  249.56 2487.54   257.4 2487.17   263.7 2487.53
   269.4 2488.33   290.1 2494.22   294.1 2495.08   314.7 2496.91   323.2 2497.92
   328.3 2498.99   334.5 2499.23   351.5 2500.69   370.7 2500.78   384.8 2501.22
#Mann= 4 ,-1,0
       0      .1       0  190.69     .05       0  249.56    .045       0
   263.7     .05       0
Bank Sta=249.56,263.7
XS Rating Curve= 0 ,0
Exp/Cntr(USF)=0,0
Exp/Cntr=0.3,0.1

Type RM Length L Ch R = 1 ,683     ,202.7,202.4,199.1
XS GIS Cut Line= 3
     2286171.298      459352.075     2285981.711      459274.652
     2285690.878      459599.233
#Sta/Elev= 30
       0 2536.01    31.5  2528.9    70.9 2518.78   110.3 2510.37   145.7 2501.42
   157.5  2499.4   177.2 2497.86   272.8 2494.97   284.8 2492.97   288.8 2492.91
   296.8 2493.51   320.7 2492.63   352.7 2492.89   364.7 2492.41   368.7 2491.95
   380.7 2489.38   392.7 2485.92   396.7 2485.54   416.7 2486.03   429.2 2485.83
   436.7 2485.32   444.7 2485.42   448.7 2485.82   464.7 2488.79   484.7 2493.23
   492.7 2494.55   500.7 2495.42   540.6 2497.91   576.6 2499.44   640.6 2500.53
#Mann= 4 ,-1,0
       0      .1       0  324.79     .05       0   429.2    .045       0
   448.7     .05       0
Bank Sta=429.2,448.7
XS Rating Curve= 0 ,0
Exp/Cntr=0.3,0.1

Type RM Length L Ch R = 1 ,481     ,125.5,134.5,142.1
XS GIS Cut Line= 4
     2286066.082      458998.7082285740.61987357459271.043145709
2285684.59841869 459365.28078686     2285546.951      459482.106
#Sta/Elev= 30
       0 2546.62    65.6 2528.47   101.6 2515.52   122.4 2506.48   127.7 2504.75
   145.1 2500.77     159 2498.34   169.4    2495   176.3 2493.58     199 2492.25
   228.2 2491.77   242.4  2490.3   273.7 2489.25   289.3 2489.42     305  2492.3
   315.5  2491.6   332.5 2492.58     409 2491.08   448.7 2486.83   458.4    2485
   475.1 2484.07   478.8 2483.48   482.7 2484.01   487.9 2484.97   531.3 2486.26
   560.8 2493.55     587 2496.53     608 2498.19   645.1 2500.08   714.5 2500.63
#Mann= 5 ,-1,0
       0      .1       0     250     .05       0   475.1    .045       0
   482.7     .05       0     684     .06       0
Bank Sta=475.1,482.7
XS Rating Curve= 0 ,0
Exp/Cntr=0.3,0.1

Type RM Length L Ch R = 1 ,346     ,169,168.2,164.7
XS GIS Cut Line= 4
2286037.60391268458967.629585512 2285637.0003426459252.356089869
2285622.10186272459252.3560898692285492.98170377459395.547035374
#Sta/Elev= 30
       0 2540.54    26.3  2532.8    55.7 2522.19    90.1 2510.66   104.8 2507.49
   124.4 2504.17     180  2497.9     223 2495.66   301.1 2493.57   314.8 2491.57
   330.5 2492.37   363.6 2491.31   394.3  2491.1   399.3 2490.79   409.1 2488.99
   428.7 2483.41   433.6 2482.58   477.8 2482.78   492.3 2481.63   500.3 2481.05
   504.3 2481.61   509.3 2482.85   533.8 2485.63   539.5 2486.79     548 2490.39
   562.1 2493.69   610.8 2496.06   624.4 2496.95   634.7 2498.24   699.2 2498.79
#Mann= 7 ,-1,0
       0     .12       0      10      .1       0      80     .05       0
     180      .1       0     200     .05       0   492.3    .045       0
   504.3     .05       0
Bank Sta=492.3,504.3
XS Rating Curve= 0 ,0
Exp/Cntr(USF)=0,0
Exp/Cntr=0.3,0.1

Type RM Length L Ch R = 1 ,178     ,97.8,97.8,97.8
XS GIS Cut Line= 4
2286026.95912396458971.6517362612285660.05215788459070.528669215
2285577.51851963459110.5697412372285511.32817608 459315.67808976
#Sta/Elev= 30
       0 2536.82    19.5 2529.52    44.3  2519.3    77.5 2509.46    85.7 2508.31
     123 2504.52   147.9 2503.22   160.3 2501.87     210 2498.86   255.6 2497.09
     268 2496.13   288.7 2493.17   321.9 2490.48   342.6 2490.94   375.7 2489.63
   388.8  2488.3     411 2484.33   415.4 2483.21  424.97 2478.99   428.8 2477.98
   433.2 2478.26   434.5 2478.97   437.7 2480.83   442.1 2482.08     478    2481
   512.3 2481.75   571.1 2486.87     588 2488.98     609 2492.76   687.3  2496.6
#Mann= 4 ,-1,0
       0      .1       0      60     .05       0  424.97    .045       0
   434.5     .05       0
Bank Sta=424.97,434.5
XS Rating Curve= 0 ,0
Exp/Cntr(USF)=0,0
Exp/Cntr=0.3,0.1

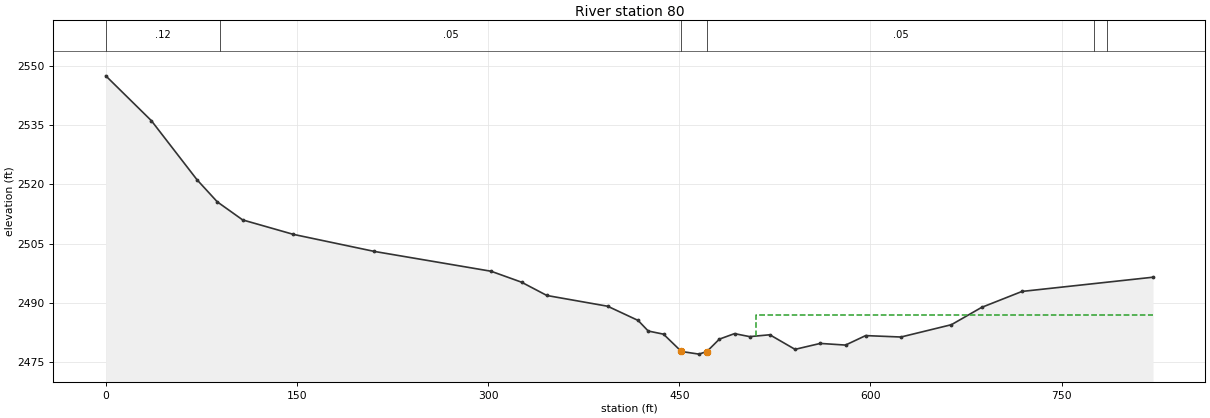
Type RM Length L Ch R = 1 ,80      ,85.6,80.1,74.9
XS GIS Cut Line= 3
     2286057.149      458921.285     2285558.862      459004.664
      2285466.55      459307.408
#Sta/Elev= 30
       0 2547.47    35.8 2536.11    71.6 2521.16    87.5 2515.57   107.4    2511
   147.2 2507.34   210.8 2503.02   302.3 2498.01   326.2 2495.24   346.1 2491.87
   393.8 2489.15   417.7 2485.55   425.6 2482.88   437.6 2482.08  451.64  2477.7
   465.4 2477.03  471.63 2477.69   481.4 2480.82   493.3 2482.22   505.2 2481.46
     521 2481.93   540.8 2478.24   560.6 2479.74   580.4 2479.32   596.2 2481.72
   623.9 2481.36   663.5 2484.48   687.2 2488.86   718.9  2492.9   821.7  2496.5
#Mann= 6 ,-1,0
       0     .12       0      90     .05       0  451.64    .045       0
  471.63     .05       0  775.21     .06       0  785.21     .05       0
#XS Ineff= 2 , 0
                          509.86         2487.03
Permanent Ineff=
       F       F
Bank Sta=451.64,471.63
XS Rating Curve= 0 ,0
Exp/Cntr=0.3,0.1
LCMann Table=0

Chan Stop Cuts=-1
Use User Specified Reach Order=0
Composite Channel Slope=5